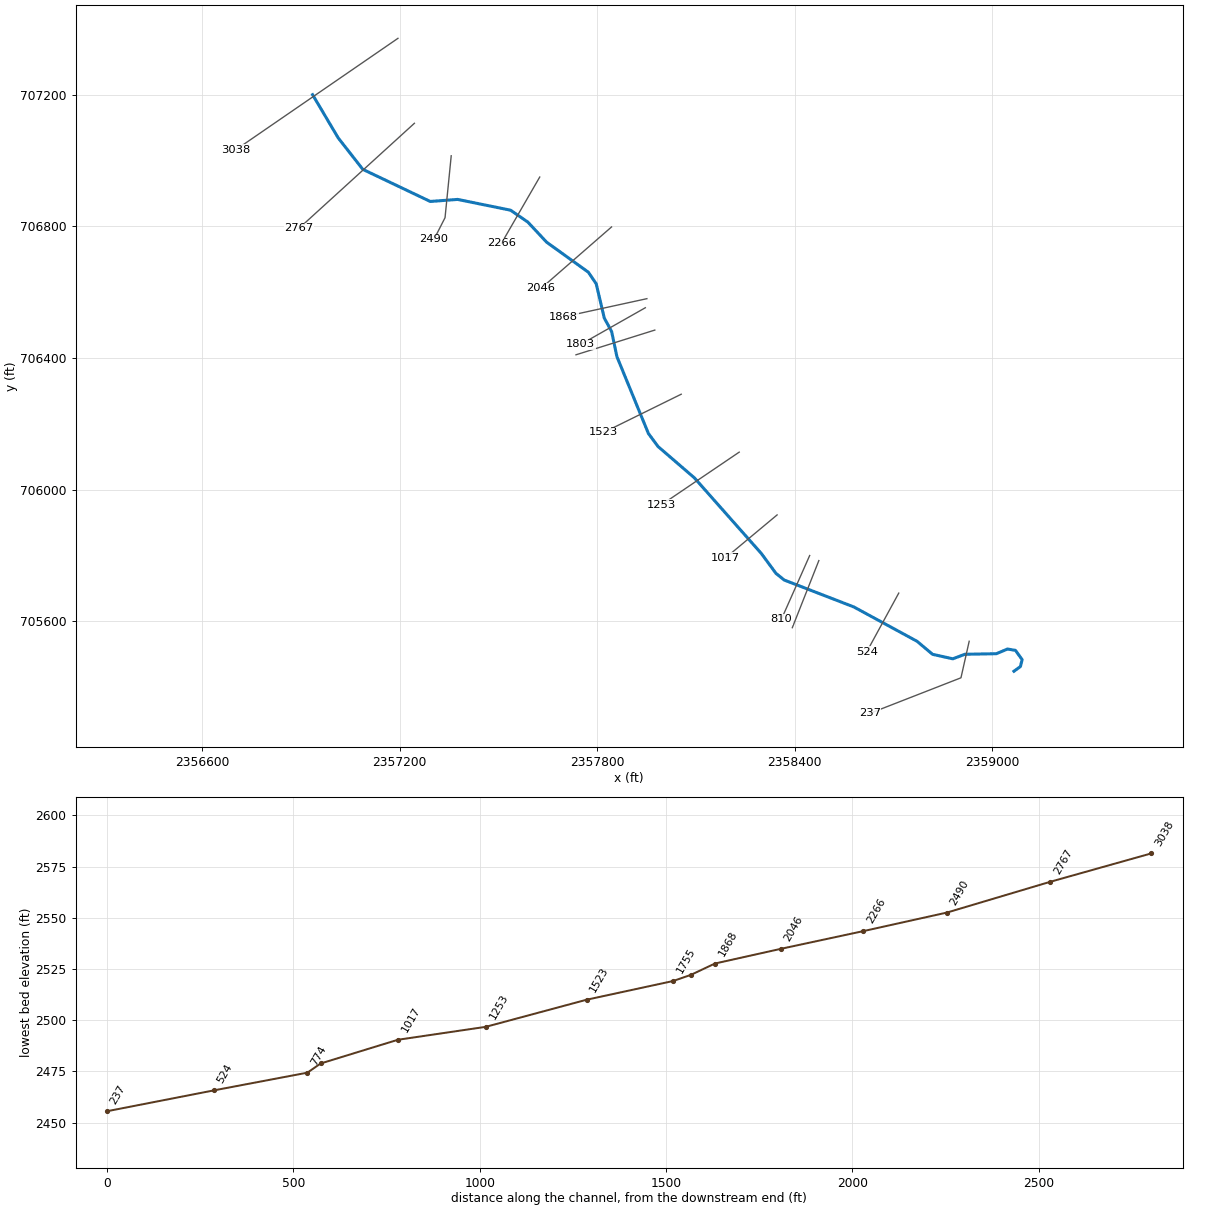
--- WOODFRDRN.prj (project) ---

Proj Title=WOODFRDRN
Current Plan=p01
Default Exp/Contr=0,0
English Units
Geom File=g01
Flow File=f01
Plan File=p01
BEGIN DESCRIPTION:
----------MODEL BY WOOD PLC 2022----------
AFH study
Randolph County, WV
HEC-RAS Version: RAS 6.2
Vertical Datum: NAVD88
Projection: NAD 1983 StatePlane West Virginia S FIPS 4702 (US Feet)
Terrain: 1-meter LIDAR (FEMA Region III 3DEP collected 2016-2018)
Land Use: 2019 NLCD
Hydrologic Method:
WV SIR2010-5033 regression equations
Additional Model Notes:
None
END DESCRIPTION:
DSS Export Rating Curves= 0
DSS Export Rating Curve Sorted= 0
DSS Export Volume Flow Curves= 0
DXF OffsetX= 0
DXF OffsetY= 0
DXF ScaleX= 0
DXF ScaleY= 0

--- WOODFRDRN.p01 (plan) ---

Plan Title=Floodplain
Program Version=6.20
Short Identifier=Floodplain
Geom File=g01
Flow File=f01
Subcritical Flow
K Sum by GR= 0
Std Step Tol= 0.01
Critical Tol= 0.01
Num of Std Step Trials= 20
Max Error Tol= 0.3
Flow Tol Ratio= 0.001
Split Flow NTrial= 30
Split Flow Tol= 0.02
Split Flow Ratio= 0.02
Log Output Level= 0
Friction Slope Method= 1
Unsteady Friction Slope Method= 2
Unsteady Bridges Friction Slope Method= 1
Parabolic Critical Depth
Global Vel Dist= 0 , 0 , 0
Global Log Level= 0
CheckData=True
Encroach Param=-1 ,0,0, 0
Mapping Interval=1HOUR
Computation Time Step Use Courant=        0
Computation Time Step Use Time Series=    0
Computation Time Step Count To Double=0
Computation Time Step Max Doubling=0
Computation Time Step Max Halving=0
Computation Time Step Residence Courant=0
Run HTab= 0
Run UNet= 0
Run Sediment= 0
Run PostProcess= 0
Run WQNet= 0
Run RASMapper=-1
UNET Theta= 0
UNET Theta Warmup= 0
UNET ZTol= 0
UNET ZSATol= 0
UNET MxIter= 0
UNET Max Iter WO Improvement= 0
UNET MaxInSteps= 0
UNET DtIC= 0
UNET DtMin= 0
UNET MaxCRTS= 0
UNET WFStab= 0
UNET SFStab= 0
UNET WFX= 1
UNET SFX= 1
UNET Gravity=32.174
UNET 1D Methodology=Finite Difference
UNET DSS MLevel= 1
UNET Pardiso=0
UNET DZMax Abort= 0
UNET Use Existing IB Tables= 0
UNET Froude Reduction=False
UNET Froude Limit= 0
UNET Froude Power= 0
UNET D1 Cores= 0
UNET WindReference=Eulerian
UNET WindDragFormulation=Hsu (1988)
UNET D2 Coriolis=0
UNET D2 Cores= 0
UNET D2 Theta= 1
UNET D2 Theta Warmup= 1
UNET D2 Z Tol= 0.01
UNET D2 Volume Tol= 0.01
UNET D2 Max Iterations= 20
UNET D2 Equation= 0
UNET D2 RampUpFraction=0.1
UNET D2 TimeSlices= 1
UNET D2 Turbulence Formulation=Non-Conservative (original)
UNET D2 Eddy Viscosity=0.3
UNET D2 Transverse Eddy Viscosity=0.1
UNET D2 Smagorinsky Mixing=0
UNET D2 BCVolumeCheck=0
UNET D2 Cores=0
UNET D2 SolverType=PARDISO (Direct)
UNET D2 Minimum Iterations= 2147483647
UNET D2 Maximum Iterations= 2147483647
UNET D2 Restart Number= 10
UNET D2 Relaxation Coeff=1.3
UNET D2 SOR Precondition Iterations= 10
UNET D2 ILUT Maximum Fill= 8
UNET D2 ILUT Tolerance=1E-08
UNET D1D2 MaxIter= 0
UNET D1D2 ZTol=0.01
UNET D1D2 QTol=0.1
UNET D1D2 MinQTol=1
Write IC File= 0
Write IC File at Fixed DateTime=0
Write IC File at Sim End=0
Echo Input=False
Echo Parameters=False
Echo Output=False
Write Detailed= 0
HDF Write Warmup=0
HDF Write Time Slices=0
HDF Flush=0
HDF Compression= 1
HDF Chunk Size= 1
HDF Spatial Parts= 1
HDF Use Max Rows=0
HDF Fixed Rows= 1
Calibration Method= 0
Calibration Iterations= 20
Calibration Max Change=0.05
Calibration Tolerance=0.2
Calibration Maximum=1.5
Calibration Minimum=0.5
Calibration Optimization Method= 1
WQ AD Non Conservative
WQ ULTIMATE=-1
WQ Max Comp Step=1HOUR
WQ Output Interval=15MIN
WQ Output Selected Increments= 0
WQ Output face flow=0
WQ Output face velocity=0
WQ Output face area=0
WQ Output face dispersion=0
WQ Output cell volume=0
WQ Output cell surface area=0
WQ Output cell continuity=0
WQ Output cumulative cell continuity=0
WQ Output face conc=0
WQ Output face dconc_dx=0
WQ Output face courant=0
WQ Output face peclet=0
WQ Output face adv mass=0
WQ Output face disp mass=0
WQ Output cell mass=0
WQ Output cell source sink temp=0
WQ Output nsm pathways=0
WQ Output nsm derived pathways=0
WQ Create Restart=0
WQ Fixed Restart=0
WQ System Summary=0
WQ Write To DSS=0
Sorting and Armoring Iterations= 10
XS Update Threshold= 0.02
Bed Roughness Predictor= 0
Hydraulics Update Threshold= 0.02
Energy Slope Method= 1
Volume Change Method= 1
Sediment Retention Method= 0
Sediment TS Multiplier= 1
Warm Up Method= 0
XS Weighting Method= 0
Number of US Weighted Cross Sections= 1
Number of DS Weighted Cross Sections= 1
Upstream XS Weight=0
Main XS Weight=1
Downstream XS Weight=0
Number of DS XS's Weighted with US Boundary= 1
Upstream Boundary Weight= 1
Weight of XSs Associated with US Boundary= 0
Number of US XS's Weighted with DS Boundary= 1
Downstream Boundary Weight= 0.5
Weight of XSs Associated with DS Boundary= 0.5
Percentile Method= 0
Sediment Output Level= 3
Mass or Volume Output= 0
Output Increment Type= 1
Profile and TS Output Increment= 1
Transport Output Increment 1
XS Output Flag= 0
XS Output Increment= 10
Read HDF5 Sediment Hotstart= 0
Sediment Hotstart Type= 0
Write Gradation File= 0
Read Gradation Hotstart= 0
Write HDF5 File= 1
Write Binary Output= 1
Write DSS Sediment File= 0
DSS Sediment Output Type= 1
SV Curve= 0
Specific Gage Flag= 0
Subcell Erosion Methods= 0
Subcell Deposition Methods= 0
Advection Scheme= 1
Matrix Solver= 0
Implicit Weighting Factor= 1
Maximum Outer Loop Convergence Iterations= 5
Convergence Maximum Absolute= 0.001
Convergence RMSE= 0.0001
Grain Fractions Max Abs Error= 0.001
Max Subgrid Regions= 1
Max Subgrid Length Scale= 3.402823E+38
Initial Layer Thickness= 3.402823E+38
Min Layer Thickness= 3.402823E+38
Max Layer Thickness= 3.402823E+38
Number of Layers= 5

--- WOODFRDRN.f01 (steady flow) ---

Flow Title=Flow
Program Version=6.20
Number of Profiles= 1
Profile Names=P100yr
River Rch & RM=WOODFRDRN,Main,3038
     458
Boundary for River Rch & Prof#=WOODFRDRN,Main            , 1
Up Type= 0
Dn Type= 3
Dn Slope=0.03564
DSS Import GetInterval= 0
DSS Import GetPeak= 0
DSS Import FillOption= 0

--- WOODFRDRN.g01 (geometry) ---

Geom Title=Geometry
Program Version=6.20

River Reach=WOODFRDRN       ,Main
Reach XY= 30
2356935.78100005707200.1580000072357013.55900002707068.908000007
2357088.34660931706973.3189274372357293.34172079706875.744835109
2357376.47770064706881.9485875962357537.25100003      706849.213
2357589.70800003706813.0900000042357646.82953666706751.994587585
     2357773.535706660.8090000152357797.41600001706625.574000001
2357821.89200002706521.6860000192357844.26957823706480.553386912
2357860.25785415706404.527503401     2357955.919706170.990999997
2357985.11196189  706131.45387352358095.66609406706036.117719054
2358298.97500002705806.4080000222358343.41999999705745.990999997
2358368.42000005705725.8520000132358580.22499998705643.908000022
2358771.89200002705539.7409999972358819.11400001705500.158000022
2358880.60015378705486.4638549222358917.46955947705500.260148664
   2359012.85428705501.9252185982359046.63141296705516.197246608
2359070.89386057705512.1535053382359091.22858661705483.995665114
2359085.92229381705462.831964099     2359066.366      705448.735

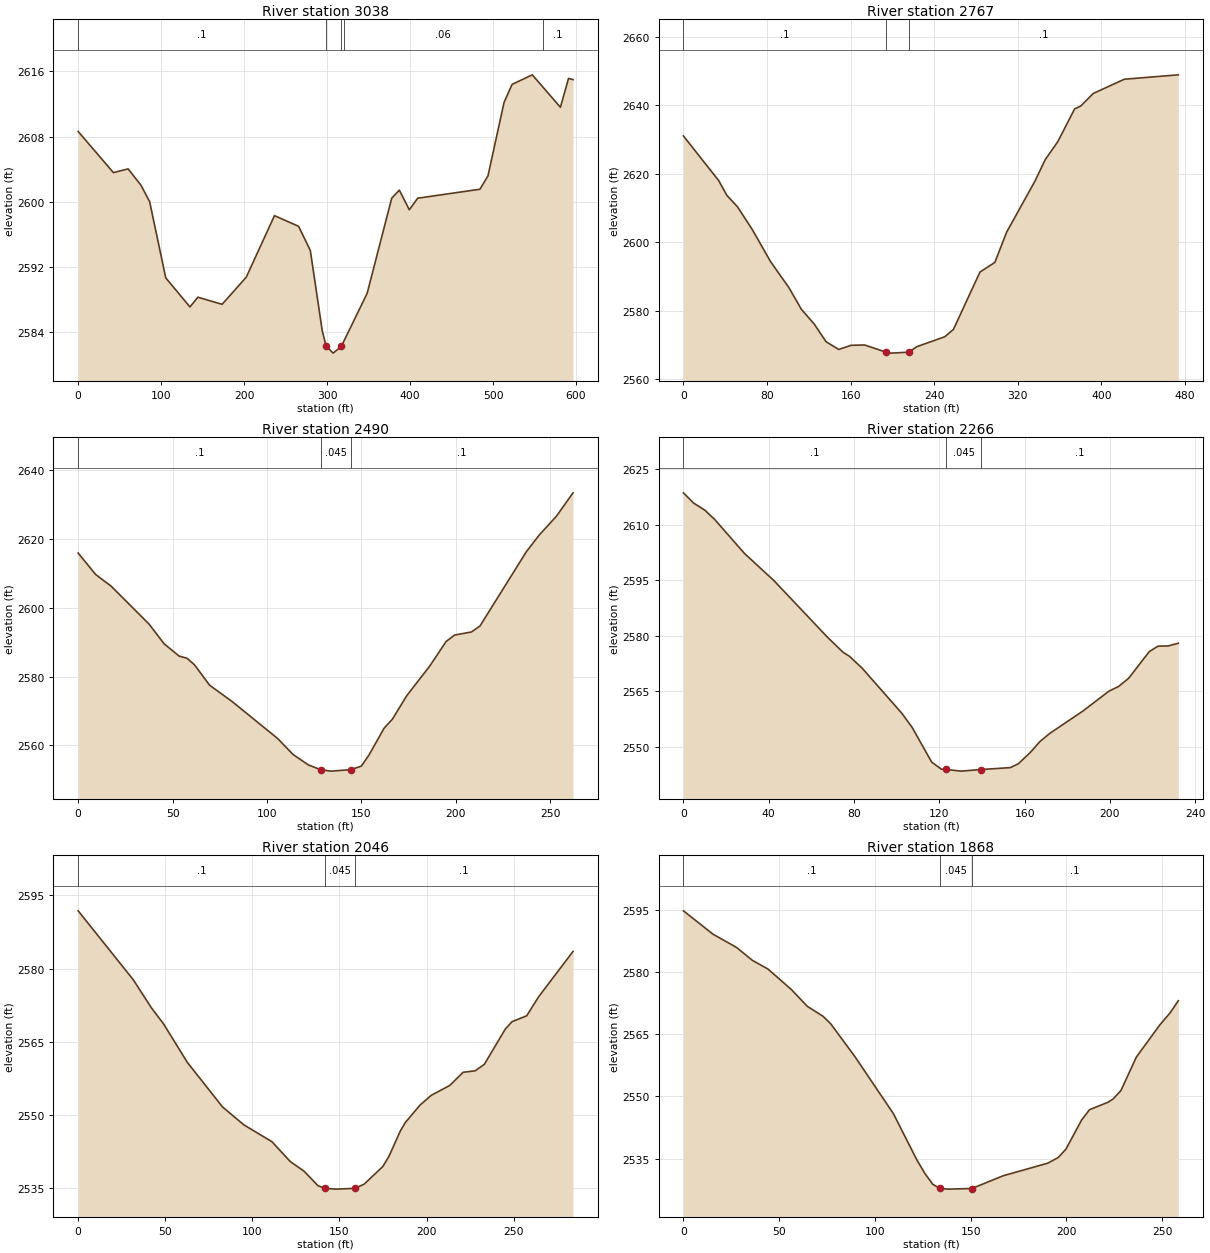
Type RM Length L Ch R = 1 ,3038    ,268.4,270.9,271.6
XS GIS Cut Line= 2
2357195.16061825707371.2735708582356703.67814125707033.409427497
#Sta/Elev= 30
       0 2608.62    42.5 2603.57    60.2 2604.03    75.6 2602.04    86.1 2600.02
   105.6 2590.65   134.7 2587.09   144.4 2588.28   173.5 2587.41   202.6 2590.74
   236.6 2598.29   265.7 2596.98   279.8 2594.01   294.2 2584.15   298.82582.292
   307.3 2581.42   317.2 2582.25   348.3 2588.76   377.9 2600.43   387.1 2601.42
   399.1 2599.01   409.2 2600.43   484.2 2601.53   493.9 2603.17   513.3 2612.19
     523  2614.4   547.3 2615.57   581.2 2611.59     591 2615.13   596.4 2614.98
#Mann= 5, -1 ,  0
       0     0.1       0   298.8   0.045       0   317.2     0.1       0
     320    0.06       0     560     0.1       0
Bank Sta=298.8,317.2
XS Rating Curve= 0 ,0
Exp/Cntr=0.3,0.1

Type RM Length L Ch R = 1 ,2767    ,268.7,277.3,282.7
XS GIS Cut Line= 2
2357245.12025827707113.2136874532356894.88616065706794.368494817
#Sta/Elev= 30
       0 2630.98    33.7 2617.97    41.6 2613.62    51.7 2610.31    66.2  2603.5
    83.2 2594.37   101.1 2586.62   112.9 2580.36   125.3    2576   136.5  2570.9
   148.6 2568.65   160.5 2569.85   173.4 2569.95  193.83 2567.86   198.9 2567.57
   215.9 2567.86   223.1 2569.42   250.1 2572.35   258.4  2574.5   283.8 2591.25
     298 2594.04   309.3 2602.88   336.7 2617.95   346.1 2623.99   358.3 2629.34
   374.4 2638.89   380.1 2639.68   392.2 2643.39   421.9 2647.54   473.6 2648.83
#Mann= 3, -1 ,  0
       0     0.1       0  193.83   0.045       0   215.9     0.1       0
Bank Sta=193.83,215.9
XS Rating Curve= 0 ,0
Exp/Cntr(USF)=0,0
Exp/Cntr=0.3,0.1

Type RM Length L Ch R = 1 ,2490    ,227.4,224.3,220.4
XS GIS Cut Line= 3
2357356.96800261707014.4626714942357338.18863309706826.445784068
2357304.96591287706761.264565535
#Sta/Elev= 30
       0 2615.98     9.3 2609.71    17.4 2606.38    37.5 2595.34    45.5  2589.6
    53.5 2585.99    57.6 2585.39    61.6 2583.48    69.6 2577.55    81.7 2572.72
   105.8 2561.96   113.8 2557.39   121.9 2554.35  128.49 2552.95   133.9 2552.54
   144.4 2552.96     150    2554     154  2557.2   162.1 2565.08   166.4 2567.63
   174.1 2574.53   186.2 2583.09   194.9 2590.26   199.4 2592.12   208.3 2593.02
   212.8 2594.74   237.4 2616.38   244.2 2621.21   253.2 2626.61   262.1 2633.49
#Mann= 3, -1 ,  0
       0     0.1       0  128.49   0.045       0   144.4     0.1       0
Bank Sta=128.49,144.4
XS Rating Curve= 0 ,0
Exp/Cntr=0.3,0.1

Type RM Length L Ch R = 1 ,2266    ,223.1,220.3,217.6
XS GIS Cut Line= 2
2357625.85402229706949.9456974132357509.76742728706748.989070746
#Sta/Elev= 30
       0 2618.57     4.7 2615.84    10.1 2613.86    14.7 2611.36    28.6 2602.23
    42.5 2594.85    67.3 2579.76    74.8 2575.58    77.9 2574.45    83.8 2571.27
   102.5 2559.04   107.3 2555.24   116.4 2545.94     121    2544   123.3 2543.92
   130.2 2543.48   139.7 2543.91   153.3 2544.43     157 2545.44   162.6 2548.46
   167.2 2551.47   171.8 2553.65   187.3 2559.67   199.5 2565.03   204.1 2566.33
   208.8 2568.53   218.5 2575.74   222.6  2577.2   227.3 2577.25   232.1 2577.99
#Mann= 3, -1 ,  0
       0     0.1       0   123.3   0.045       0   139.7     0.1       0
Bank Sta=123.3,139.7
XS Rating Curve= 0 ,0
Exp/Cntr(USF)=0,0
Exp/Cntr=0.3,0.1

Type RM Length L Ch R = 1 ,2046    ,181.5,177.9,173.1
XS GIS Cut Line= 2
 2357844.0166838706798.3586386342357629.83736205706611.734797073
#Sta/Elev= 30
       0 2591.81    31.6 2577.73    42.2 2571.88    48.9 2568.75    62.7 2560.79
    82.9 2551.68    95.3 2547.98   111.2 2544.59   121.8  2540.5   129.7 2538.54
   137.7 2535.57   141.8 2535.02   148.1 2534.87     159 2535.03   164.3 2535.92
   174.9  2539.5   178.4 2541.56     185 2546.79   187.8 2548.49   196.3 2552.08
   202.7 2554.06   213.4  2556.1     221 2558.78   227.9 2559.07   233.2 2560.41
   245.3 2567.66   249.1 2569.13   257.5 2570.33   264.4 2574.25   284.1  2583.5
#Mann= 3, -1 ,  0
       0     0.1       0   141.8   0.045       0     159     0.1       0
Bank Sta=141.8,159
XS Rating Curve= 0 ,0
Exp/Cntr=0.3,0.1

Type RM Length L Ch R = 1 ,1868    ,62.9,64.4,67.2
XS GIS Cut Line= 2
2357951.38448291706580.470783314  2357698.787024706525.368529859
#Sta/Elev= 30
       0 2594.71    15.4  2589.1    27.8 2585.87      36 2582.78    44.2 2580.67
    56.5 2575.69    64.7 2571.69    72.9 2569.31      77 2567.45    89.5 2559.63
   109.7 2545.82     122 2534.62   126.1 2531.45   130.2 2528.83  133.98 2527.81
   138.4 2527.65   150.7  2527.8     167 2530.87   190.3  2533.9   195.7 2535.24
   199.8 2537.28     208 2544.31   212.1 2546.79   221.9 2548.61   224.4 2549.36
   228.5 2551.38   236.6 2559.48   248.9 2567.25   254.2 2570.12   258.5 2573.04
#Mann= 3, -1 ,  0
       0     0.1       0  133.98   0.045       0   150.7     0.1       0
Bank Sta=133.98,150.7
XS Rating Curve= 0 ,0
Exp/Cntr(USF)=0,0
Exp/Cntr=0.3,0.1

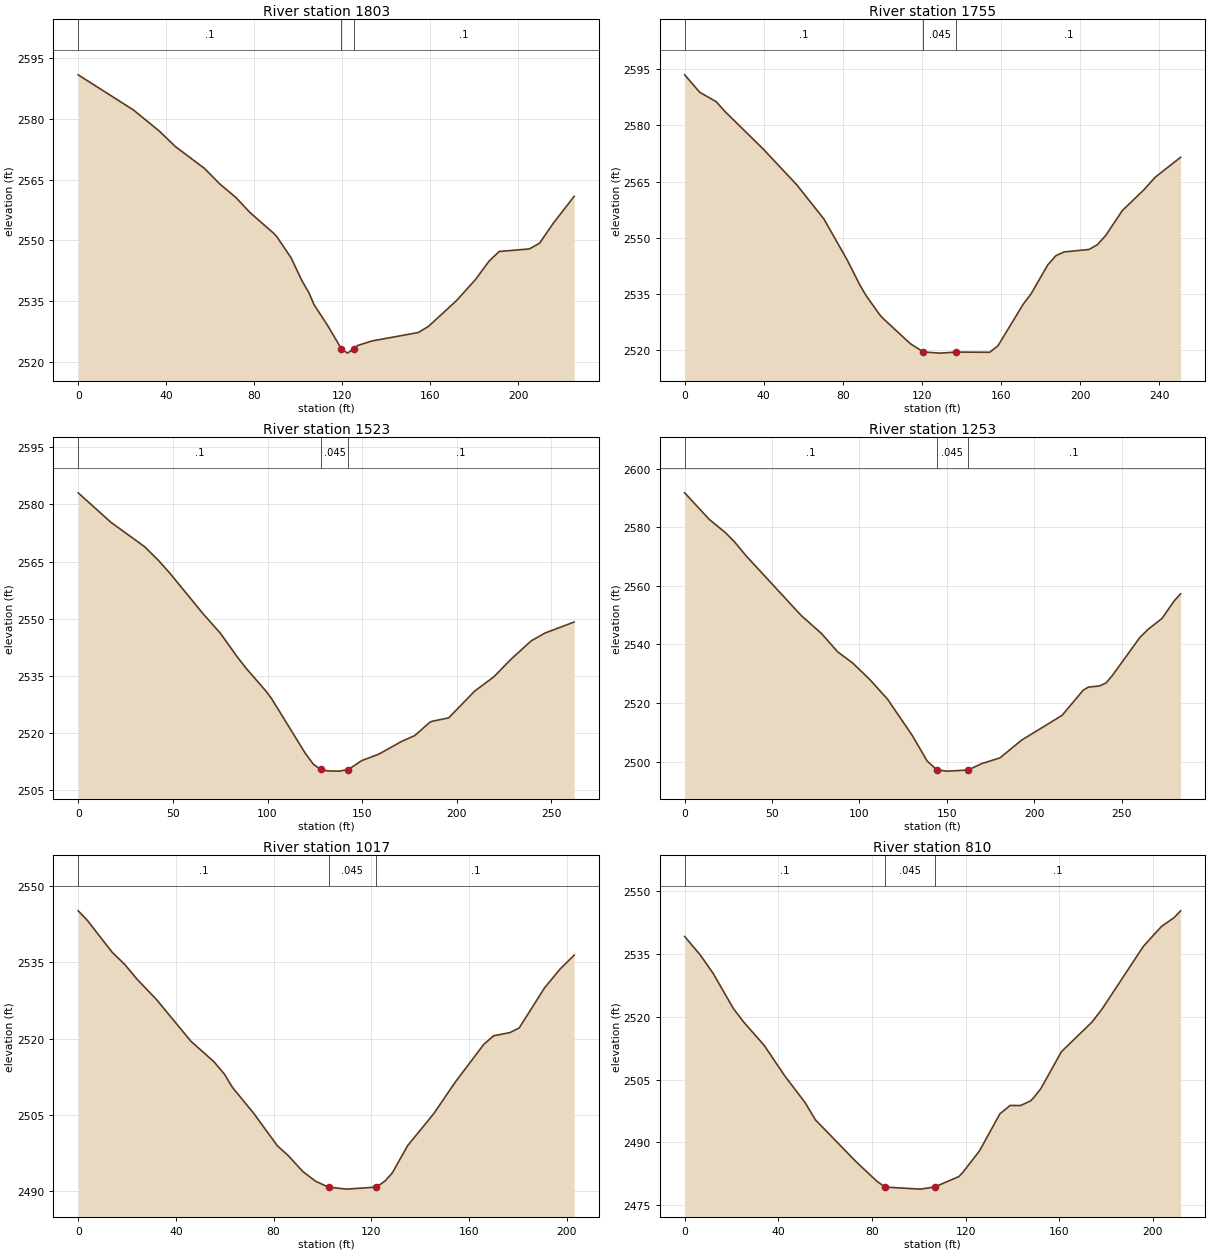
Type RM Length L Ch R = 1 ,1803    ,48.5,47.9,48.2
XS GIS Cut Line= 2
2357946.62698013706552.9102602442357750.56770951706441.758547769
#Sta/Elev= 30
       0 2590.96    25.1 2582.27    36.8 2577.07    44.2  2573.2    57.4  2567.8
    64.3 2563.99    71.8 2560.56    77.9 2556.98    88.7 2551.83    90.2 2550.98
    96.8 2545.66   101.4 2540.33   104.9 2536.99   107.2 2534.09   113.2  2529.1
  119.65 2523.17   122.4 2522.12  125.14  2523.2     127 2524.01   133.7 2525.15
   154.6 2527.22   159.2 2528.74   171.8 2535.04   180.6 2540.34   186.7 2544.86
   191.3 2547.26   205.1  2547.9   209.7 2549.32   215.8 2554.16   225.4  2560.9
#Mann= 3, -1 ,  0
       0     0.1       0  119.65   0.045       0  125.14     0.1       0
Bank Sta=119.65,125.14
XS Rating Curve= 0 ,0
Exp/Cntr(USF)=0,0
Exp/Cntr=0.3,0.1

Type RM Length L Ch R = 1 ,1755    ,230.7,232.1,233
XS GIS Cut Line= 2
2357975.41672533706485.0476592862357735.99543949706409.981579568
#Sta/Elev= 30
       0 2593.55     7.6 2588.89      16 2586.35    20.2 2583.84    39.7 2573.72
    56.7 2564.14    70.5 2554.94    82.3 2543.95    88.6 2537.37    91.8 2534.48
    98.2 2529.72    99.8 2528.67   114.2 2521.62   120.8 2519.42   129.2 2519.11
   137.5 2519.39   154.3 2519.34   158.5 2521.07   171.1 2532.06   175.3 2535.02
   183.7 2542.72   187.8 2545.18     192 2546.18   204.6 2546.84   208.8 2548.12
     213 2550.57   221.4 2557.24   232.3 2562.79   238.1 2566.19   250.9  2571.5
#Mann= 3, -1 ,  0
       0     0.1       0   120.8   0.045       0   137.5     0.1       0
Bank Sta=120.8,137.5
XS Rating Curve= 0 ,0
Exp/Cntr(USF)=0,0
Exp/Cntr=0.3,0.1

Type RM Length L Ch R = 1 ,1523    ,269.1,270.2,270.8
XS GIS Cut Line= 2
2358055.69256332706290.2568732112357820.72518296706174.447288674
#Sta/Elev= 30
       0 2583.05    17.3  2575.3    35.1  2568.9    42.3 2565.35    48.5  2561.9
    66.2 2551.16    75.3 2546.06    84.1 2539.91    88.7 2536.99      99 2531.09
   102.1 2529.06   119.9  2514.7   124.3 2511.73   128.22510.399   131.9 2510.02
   137.9 2509.97   142.72510.393   149.8 2512.74   158.8 2514.42   170.7 2517.74
   177.8 2519.31   185.6 2522.73   186.8 2523.04   195.7 2523.95   209.5 2531.02
   219.6 2534.74   228.6 2539.33   239.4 2544.21   246.7 2546.25     262 2549.12
#Mann= 3, -1 ,  0
       0     0.1       0   128.2   0.045       0   142.7     0.1       0
Bank Sta=128.2,142.7
XS Rating Curve= 0 ,0
Exp/Cntr=0.3,0.1

Type RM Length L Ch R = 1 ,1253    ,234.8,235.9,236.5
XS GIS Cut Line= 2
2358231.76193691706114.2652787882357996.84076389705955.173091996
#Sta/Elev= 30
       0 2591.78      14 2582.75    23.5 2578.07    28.5 2575.06      35 2570.36
    66.7 2549.87    78.3 2543.73    87.5  2537.5    96.1 2533.66   105.8  2528.1
   116.1 2521.27   130.1 2509.02   138.7  2500.2   144.4 2497.12   150.3 2496.75
   161.8 2497.11   170.4 2499.41   180.3 2501.25   192.7 2507.32   215.9  2515.8
     228  2524.4   230.9 2525.43   237.3 2525.84     241 2526.84   244.5 2529.27
   260.4 2542.41   265.2 2545.22     273 2548.86   280.1 2554.94   283.7 2557.29
#Mann= 3, -1 ,  0
       0     0.1       0   144.4   0.045       0   161.8     0.1       0
Bank Sta=144.4,161.8
XS Rating Curve= 0 ,0
Exp/Cntr(USF)=0,0
Exp/Cntr=0.3,0.1

Type RM Length L Ch R = 1 ,1017    ,201.9,207.2,211.4
XS GIS Cut Line= 2
2358346.87624699 705923.55172329 2358190.8662717705793.526710623
#Sta/Elev= 30
       0 2545.12     3.6 2543.33    13.9 2536.99    19.1 2534.56    24.3 2531.58
      32 2527.72    46.2 2519.47    55.6 2515.46    59.9 2513.01    63.2  2510.4
    71.8 2505.37    81.6 2498.93      86 2497.03      92 2493.88    97.2 2491.99
   102.5 2490.82   109.9 2490.43   122.12490.834   125.7 2492.04   128.6  2493.6
   134.9 2498.97   145.6 2505.26   154.5 2511.52   166.1 2518.88   170.1 2520.56
   176.8 2521.19   180.6 2522.11     191    2530   197.4 2533.71   203.1 2536.41
#Mann= 3, -1 ,  0
       0     0.1       0   102.5   0.045       0   122.1     0.1       0
Bank Sta=102.5,122.1
XS Rating Curve= 0 ,0
Exp/Cntr=0.3,0.1

Type RM Length L Ch R = 1 ,810     ,35.3,35.6,36.1
XS GIS Cut Line= 3
2358445.84102771705800.2366493022358427.94370667705759.788703762
2358359.93388674705606.587635699
#Sta/Elev= 30
       0 2539.16     6.6  2534.8    12.1 2530.41    20.8 2521.96    25.2 2518.74
      34 2513.14    42.7 2505.92    51.5 2499.45    55.8 2495.41    73.3 2485.34
    82.1 2480.72    85.6 2479.34   100.6 2478.85   106.7 2479.35   117.1 2481.85
   118.8 2482.86   125.9 2487.97   134.6 2496.81     139 2498.83   143.4  2498.8
   147.7  2499.9   149.1 2500.72   152.1 2502.83   160.9 2511.67     174 2518.76
   178.4 2521.97   195.9 2536.82   203.6 2541.55     209 2543.66   211.8 2545.29
#Mann= 3, -1 ,  0
       0     0.1       0    85.6   0.045       0   106.7     0.1       0
Bank Sta=85.6,106.7
XS Rating Curve= 0 ,0
Exp/Cntr(USF)=0,0
Exp/Cntr=0.3,0.1

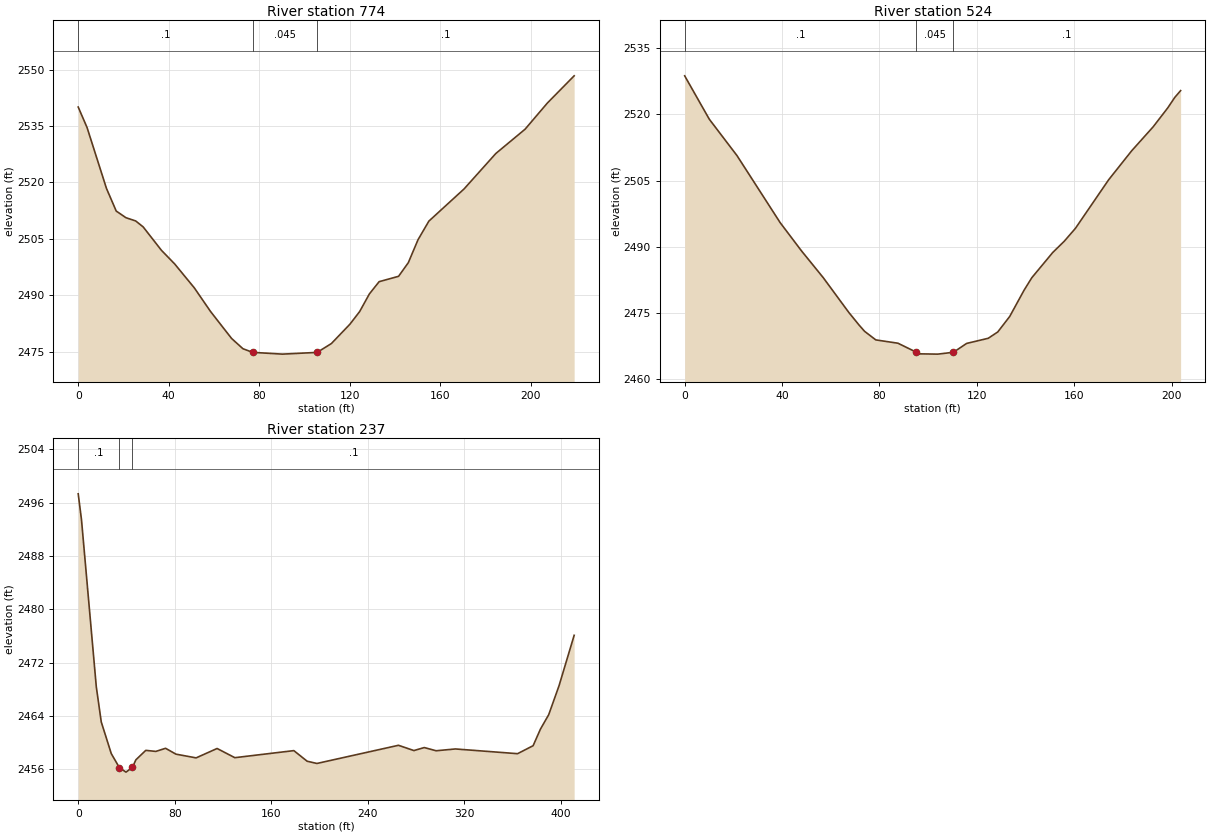
Type RM Length L Ch R = 1 ,774     ,251.6,250.3,249
XS GIS Cut Line= 2
2358473.69391071705784.8408553172358393.09664617705580.977186187
#Sta/Elev= 30
       0 2540.06     3.9 2534.63    12.5 2518.41    16.8 2512.41    21.1 2510.64
    25.4 2509.78    28.7  2508.2    36.8 2501.96    42.6 2498.37    51.3    2492
    58.5  2485.7    67.8 2478.53    72.8 2475.81    77.1 2474.84    90.3 2474.37
  105.61 2474.83   111.9 2477.18   120.1 2482.33   124.4 2485.69   128.7 2490.38
     133 2493.63   141.6 2495.06   145.9 2498.68   150.2 2504.79     155 2509.74
   170.5 2518.26   184.6 2527.72   197.5 2534.16   207.4 2541.15   219.2 2548.36
#Mann= 3, -1 ,  0
       0     0.1       0    77.1   0.045       0  105.61     0.1       0
Bank Sta=77.1,105.61
XS Rating Curve= 0 ,0
Exp/Cntr(USF)=0,0
Exp/Cntr=0.3,0.1

Type RM Length L Ch R = 1 ,524     ,284.8,287.3,288.2
XS GIS Cut Line= 2
2358716.40936265705686.0831372812358618.94247527705507.251151261
#Sta/Elev= 30
       0 2528.74    10.1 2518.93    21.5 2510.67    39.2 2495.52      48  2489.1
    56.9 2483.06    67.4 2475.19    71.6 2472.34    73.9  2470.9    78.5 2468.96
    87.6 2468.21    95.2 2466.16    96.7  2465.8     104 2465.74   110.4 2466.16
   115.8 2468.16   124.7 2469.33   128.6 2470.76   133.5 2474.26   139.4 2480.21
   142.6 2483.05   151.2 2488.76   155.9 2491.29   160.5 2494.22   174.1 2505.18
   183.6 2511.77   192.4 2517.18   198.4 2521.47   201.3 2523.85   203.7 2525.39
#Mann= 3, -1 ,  0
       0     0.1       0    95.2   0.045       0   110.4     0.1       0
Bank Sta=95.2,110.4
XS Rating Curve= 0 ,0
Exp/Cntr=0.3,0.1

Type RM Length L Ch R = 1 ,237     ,,,
XS GIS Cut Line= 3
2358930.38917672705539.764875996 2358905.4038568 705428.78461043
2358628.52646571705320.722404095
#Sta/Elev= 30
       0 2497.34     2.7 2493.48      15 2468.34    19.1 2463.08    27.4 2458.32
   34.11 2456.22    39.6 2455.54    44.9 2456.25    47.8 2457.39      56 2458.81
    64.3 2458.65    72.4 2459.12      81 2458.24    97.7 2457.68   115.1 2459.09
   129.8 2457.71   178.7 2458.77   189.7 2457.18   197.8 2456.84   265.4 2459.57
   278.2 2458.78   286.8 2459.23   296.6 2458.75   312.6 2459.02   364.1 2458.31
     377 2459.51   383.1 2462.01   389.9 2464.16   398.5 2468.53     411 2476.09
#Mann= 3, -1 ,  0
       0     0.1       0   34.11   0.045       0    44.9     0.1       0
Bank Sta=34.11,44.9
XS Rating Curve= 0 ,0
Exp/Cntr(USF)=0,0
Exp/Cntr=0.3,0.1
LCMann Table=0

Chan Stop Cuts=-1
Use User Specified Reach Order=0
Composite Channel Slope=5